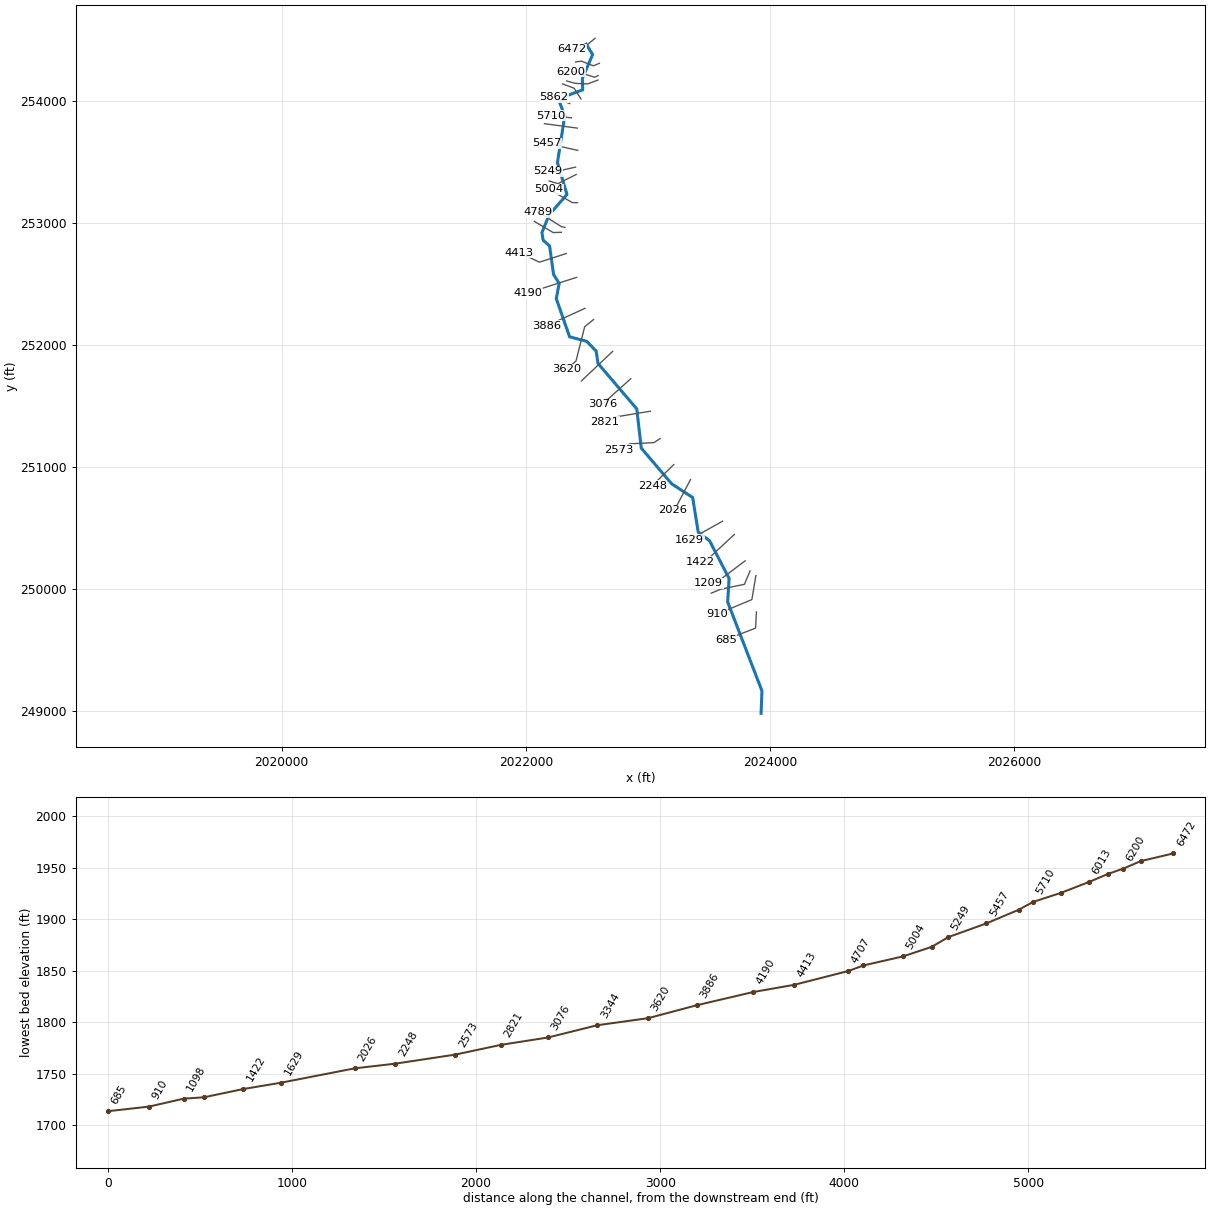
--- BIGCK_T1.prj (project) ---

Proj Title=BIGCK_T1
Current Plan=p01
Default Exp/Contr=0,0
English Units
Geom File=g01
Flow File=f01
Plan File=p01
BEGIN DESCRIPTION:
Stream Name: Big Creek Tributary 1
Flood Zone: Approximate
Summers County, West Virginia
HEC-RAS Version: 5.0.7
Hydrology Method:
regression up to Q100=1723, gage weighting at Q100=1723 through the tie in
Model Notes:
coincident peak with BIGCK_2, KWSEL tie-in/shared XS with BIGCK_1
The 100 plus and 500-yr profiles are crossing where hydrology methodology switches from regression to gage weighting
END DESCRIPTION:
DSS Export Rating Curves= 0
DSS Export Rating Curve Sorted= 0
DSS Export Volume Flow Curves= 0
DXF OffsetX= 0
DXF OffsetY= 0
DXF ScaleX= 0
DXF ScaleY= 0

--- BIGCK_T1.p01 (plan) ---

Plan Title=Floodplain
Program Version=5.07
Short Identifier=Floodplain
Geom File=g01
Flow File=f01
Subcritical Flow
K Sum by GR= 0
Std Step Tol= 0.01
Critical Tol= 0.01
Num of Std Step Trials= 20
Max Error Tol= 0.3
Flow Tol Ratio= 0.001
Split Flow NTrial= 30
Split Flow Tol= 0.02
Split Flow Ratio= 0.02
Log Output Level= 0
Friction Slope Method= 1
Unsteady Friction Slope Method= 2
Unsteady Bridges Friction Slope Method= 1
Parabolic Critical Depth
Global Vel Dist= 0 , 0 , 0
Global Log Level= 0
CheckData=True
Encroach Param=-1 ,0,0, 0
Mapping Interval=1HOUR
Computation Time Step Use Courant=        0
Computation Time Step Use Time Series=    0
Computation Time Step Count To Double=0
Computation Time Step Max Doubling=0
Computation Time Step Max Halving=0
Computation Time Step Residence Courant=0
Run HTab= 0
Run UNet= 0
Run Sediment= 0
Run PostProcess= 0
Run WQNet= 0
Run RASMapper= 0
UNET Theta= 0
UNET Theta Warmup= 0
UNET ZTol= 0
UNET ZSATol= 0
UNET MxIter= 0
UNET Max Iter WO Improvement= 0
UNET MaxInSteps= 0
UNET DtIC= 0
UNET DtMin= 0
UNET MaxCRTS= 0
UNET WFStab= 0
UNET SFStab= 0
UNET WFX= 1
UNET SFX= 1
UNET 1D Methodology=Finite Difference
UNET DSS MLevel= 1
UNET Pardiso=0
UNET DZMax Abort= 0
UNET Use Existing IB Tables= 0
UNET Froude Reduction=False
UNET Froude Limit= 0
UNET Froude Power= 0
UNET D1 Cores= 0
UNET D2 Coriolis=0
UNET D2 Cores= 0
UNET D2 Theta= 1
UNET D2 Theta Warmup= 1
UNET D2 Z Tol= 0.01
UNET D2 Volume Tol= 0.01
UNET D2 Max Iterations= 20
UNET D2 Equation= 0
UNET D2 RampUpFraction=0.1
UNET D2 TimeSlices= 1
UNET D2 BCVolumeCheck=0
UNET D1D2 MaxIter= 0
UNET D1D2 ZTol=0.01
UNET D1D2 QTol=0.1
UNET D1D2 MinQTol=1
Write IC File= 0
Write IC File at Fixed DateTime=0
Write IC File at Sim End=0
Echo Input=False
Echo Parameters=False
Echo Output=False
Write Detailed= 0
HDF Write Warmup=0
HDF Write Time Slices=0
HDF Flush=0
HDF Face Node Velocities=0
HDF Compression= 1
HDF Chunk Size= 1
HDF Spatial Parts= 1
HDF Use Max Rows=0
HDF Fixed Rows= 1
Calibration Method= 0
Calibration Iterations= 20
Calibration Max Change=0.05
Calibration Tolerance=0.2
Calibration Maximum=1.5
Calibration Minimum=0.5
Calibration Optimization Method= 1
WQ AD Non Conservative
WQ ULTIMATE=-1
WQ Max Comp Step=1HOUR
WQ Output Interval=15MIN
WQ Output Selected Increments= 0
WQ Output face flow=0
WQ Output face velocity=0
WQ Output face area=0
WQ Output face dispersion=0
WQ Output cell volume=0
WQ Output cell surface area=0
WQ Output cell continuity=0
WQ Output cumulative cell continuity=0
WQ Output face conc=0
WQ Output face dconc_dx=0
WQ Output face courant=0
WQ Output face peclet=0
WQ Output face adv mass=0
WQ Output face disp mass=0
WQ Output cell mass=0
WQ Output cell source sink temp=0
WQ Output nsm pathways=0
WQ Output nsm derived pathways=0
WQ Output MaxMinRange=-1
WQ Daily Max Min Mean=-1
WQ Daily Range=0
WQ Daily Time=0
WQ Create Restart=0
WQ Fixed Restart=0
WQ System Summary=0
WQ Write To DSS=0
WQ Use Fixed Temperature=0
Sorting and Armoring Iterations= 10
XS Update Threshold= 0.02
Bed Roughness Predictor= 0
Hydraulics Update Threshold= 0.02
Energy Slope Method= 1
Volume Change Method= 1
Sediment Retention Method= 0
XS Weighting Method= 0
Number of US Weighted Cross Sections= 1
Number of DS Weighted Cross Sections= 1
Upstream XS Weight=0
Main XS Weight=1
Downstream XS Weight=0
Number of DS XS's Weighted with US Boundary= 1
Upstream Boundary Weight= 1
Weight of XSs Associated with US Boundary= 0
Number of US XS's Weighted with DS Boundary= 1
Downstream Boundary Weight= 0.5
Weight of XSs Associated with DS Boundary= 0.5
Percentile Method= 0
Sediment Output Level= 3
Mass or Volume Output= 0
Output Increment Type= 1
Profile and TS Output Increment= 1
XS Output Flag= 0
XS Output Increment= 10
Write Gradation File= 0
Read Gradation Hotstart= 0
Write HDF5 File= 1
Write Binary Output= 1
Write DSS Sediment File= 0
SV Curve= 0
Specific Gage Flag= 0

--- BIGCK_T1.f01 (steady flow) ---

Flow Title=Flows
Program Version=5.07
Number of Profiles= 6
Profile Names=01pct,10pct,04pct,02pct,0_2pct,01plus
River Rch & RM=BIGCK_T1,Main            ,6472
     518     273     363     438     725     766
River Rch & RM=BIGCK_T1,Main            ,5710
     605     320     426     512     844     895
River Rch & RM=BIGCK_T1,Main            ,4413
    1723     788    1120    1409    2629    2452
River Rch & RM=BIGCK_T1,Main            ,0
    2463    1138    1610    2014    3720    3506
Boundary for River Rch & Prof#=BIGCK_T1,Main            , 1
Up Type= 0
Dn Type= 1
Dn Known WS=1698.3
Boundary for River Rch & Prof#=BIGCK_T1,Main            , 2
Up Type= 0
Dn Type= 1
Dn Known WS=1696.6
Boundary for River Rch & Prof#=BIGCK_T1,Main            , 3
Up Type= 0
Dn Type= 1
Dn Known WS=1697.1
Boundary for River Rch & Prof#=BIGCK_T1,Main            , 4
Up Type= 0
Dn Type= 1
Dn Known WS=1697.7
Boundary for River Rch & Prof#=BIGCK_T1,Main            , 5
Up Type= 0
Dn Type= 1
Dn Known WS=1700.2
Boundary for River Rch & Prof#=BIGCK_T1,Main            , 6
Up Type= 0
Dn Type= 1
Dn Known WS=1699.9
DSS Import GetInterval= 0
DSS Import GetPeak= 0
DSS Import FillOption= 0

--- BIGCK_T1.g01 (geometry) ---

Geom Title=Geometry
Program Version=5.07

River Reach=BIGCK_T1        ,Main
Reach XY= 30
     2022495.185254462.8680000162022547.34300001254377.191000015
2022463.03400001254181.1089999972022466.22700001254088.496999994
2022333.35400003      254039.6912022278.44800001253980.556000009
2022319.32600002253878.3639999932022259.28699999253492.586999997
2022337.20900002253231.3569999932022191.58499999253065.932999998
     2022132.185252919.0310000182022142.40500003252855.800000012
     2022194.778252810.4520000072022227.35200001252576.686000019
2022273.33900002252501.9580000042022249.70700002 252378.04900001
2022358.71900001252065.4810000062022498.72551125252028.302383453
2022576.28300001251948.7570000142022591.20724897251847.633183555
2022908.84900002251474.9230000082022945.89400002251153.655000016
2023194.45600004250861.462000012 2023366.8070201250749.048065156
     2023412.215250465.4530000092023505.39799999250394.236000001
     2023665.294250086.3520000132023653.57700001249893.493000001
2023934.28770421249165.0413996282023927.23448477248980.838642197

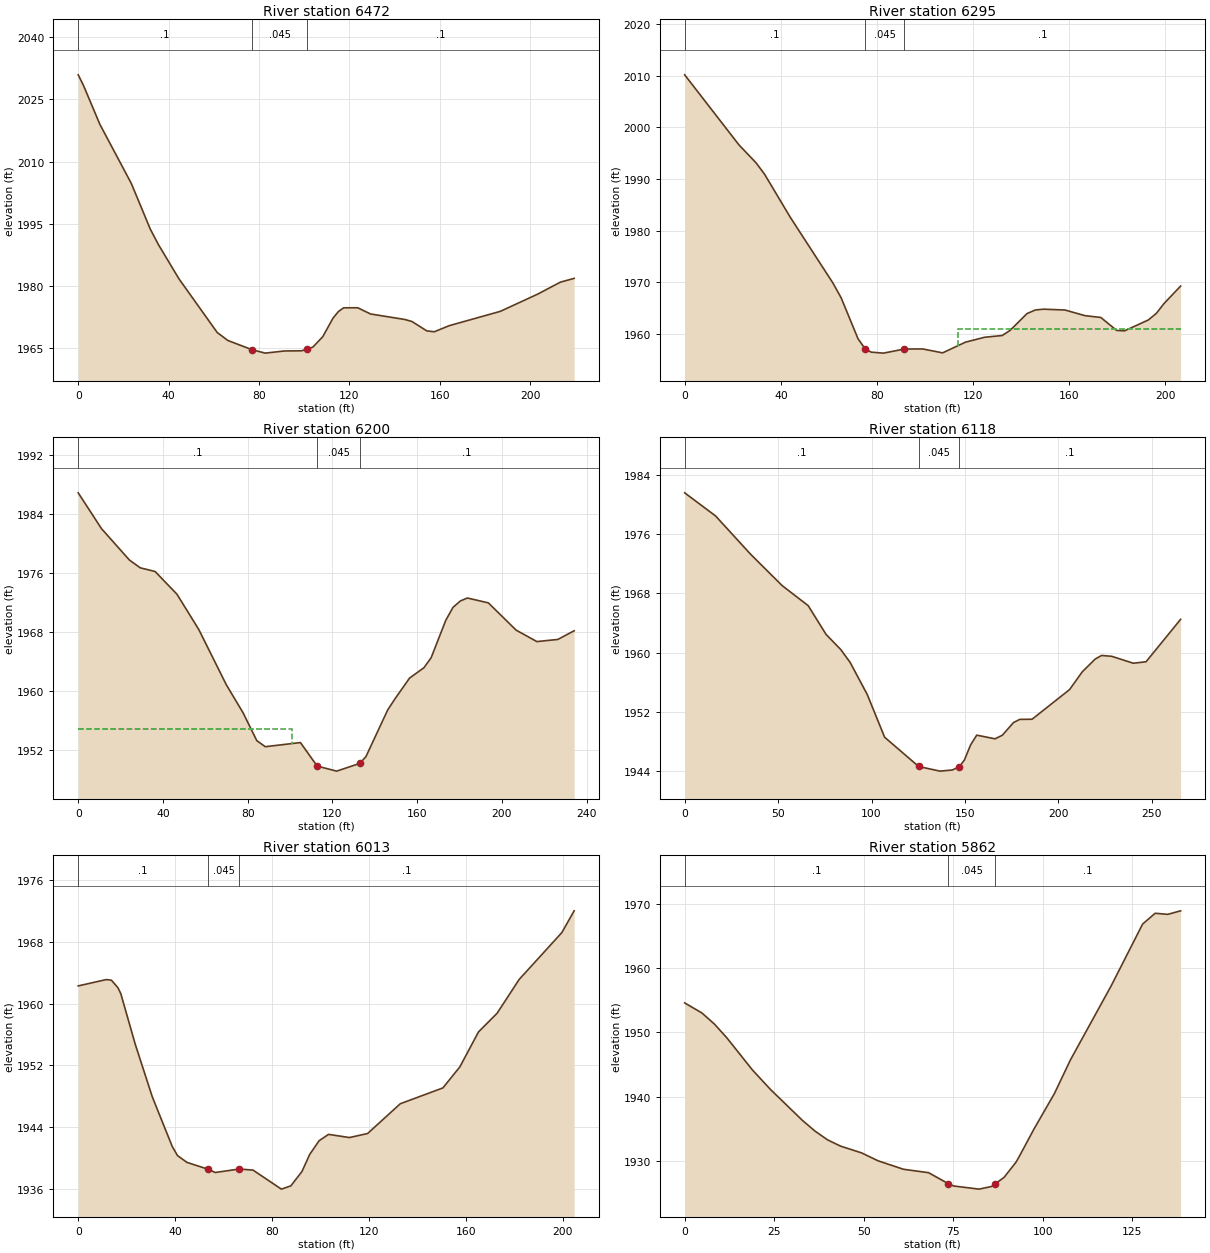
Type RM Length L Ch R = 1 ,6472    ,177.6,177.7,177.6
XS GIS Cut Line= 3
2022567.54671921254510.4035084952022460.54976266254423.013724199
2022379.19544892 254422.44896492
#Sta/Elev= 30
       0 2030.93     2.3 2028.41     9.6 2018.98    23.5 2004.74    31.9 1993.73
    35.5 1989.99    44.6 1981.73    61.5 1968.81    66.2 1966.88      77 1964.63
    82.8 1963.82    91.2 1964.34    98.8 1964.38   101.41964.733   103.9  1965.3
   108.2 1967.75   112.8 1972.28   115.2 1973.87   117.5 1974.75   123.7 1974.76
   129.4 1973.26   144.5 1971.94   147.7 1971.45   154.3 1969.18   157.6 1968.97
   164.2 1970.44   186.8 1973.89   203.3 1978.03   213.4 1980.93   219.5 1981.85
#Mann= 3 ,-1 , 0
       0      .1       0      77    .045       0   101.4      .1       0
Bank Sta=77,101.4
XS Rating Curve= 0 ,0
Exp/Cntr=0.3,0.1

Type RM Length L Ch R = 1 ,6295    ,92.9,94.8,96.2
XS GIS Cut Line= 4
2022603.03506338254305.733661501 2022554.2743996254285.457665006
 2022455.8868454254323.2272948182022408.15510443254317.359153558
#Sta/Elev= 30
       0 2010.16    22.6  1996.6    29.7 1993.13    33.2 1990.96    43.9 1982.63
    61.6 1969.94    65.1 1967.02    72.1 1959.12    75.21957.076    77.6 1956.52
    82.7 1956.33    91.4 1957.12      99 1957.14   107.3 1956.38   116.8 1958.45
   124.8  1959.4   132.1 1959.74   135.4 1960.74   142.4 1963.98   145.9 1964.68
   149.4 1964.83   158.2 1964.67   166.5 1963.58   173.1 1963.23   179.7 1960.72
     183 1960.64   192.9 1962.75   196.2 1964.02   199.5 1965.98   206.3  1969.3
#Mann= 3 ,-1 , 0
       0      .1       0    75.2    .045       0    91.4      .1       0
#XS Ineff= 2 , 0
                           113.5            1961
Permanent Ineff=
       F       F
Bank Sta=75.2,91.4
XS Rating Curve= 0 ,0
Exp/Cntr(USF)=0,0
Exp/Cntr=0.3,0.1

Type RM Length L Ch R = 1 ,6200    ,77.9,82,85.7
XS GIS Cut Line= 4
2022592.02143933254205.387309014 2022564.5245788254191.682186932
2022420.05580226254235.8726136182022367.77181624254236.592577166
#Sta/Elev= 30
       0 1986.88      11 1982.01    24.2 1977.74    29.3 1976.69    36.3 1976.19
    46.6 1973.11    56.9 1968.32    69.9 1960.81    77.8 1957.01    84.3 1953.21
    88.3 1952.39   104.9 1952.95   112.81949.755     122 1949.07   132.9 1950.12
   135.8 1951.03   146.1 1957.39   149.5 1958.88   156.4 1961.71   163.2 1963.12
   166.6 1964.48   173.5 1969.56   176.9 1971.31   180.4 1972.19   183.7 1972.59
   193.6 1971.93   206.7 1968.23   216.5 1966.67   226.4 1966.96   234.1 1968.14
#Mann= 3 ,-1 , 0
       0      .1       0   112.8    .045       0   132.9      .1       0
#XS Ineff= 2 , 0
          100.94 1954.74
Permanent Ineff=
       F       F
Bank Sta=112.8,132.9
XS Rating Curve= 0 ,0
Exp/Cntr(USF)=0,0
Exp/Cntr=0.3,0.1

Type RM Length L Ch R = 1 ,6118    ,116,105.1,90.1
XS GIS Cut Line= 4
2022591.67149299254168.8131483352022505.64718741254137.085717797
2022404.86593741254141.7298150062022334.72704858254161.174259439
#Sta/Elev= 30
       0 1981.61    16.5 1978.49    35.4 1973.27    52.1 1969.07    66.1 1966.34
    75.7 1962.44    83.5 1960.41    88.5 1958.68    97.7 1954.32     107 1948.54
   125.2 1944.58   136.6 1943.95   143.2  1944.1     147 1944.55   149.7 1945.46
     153 1947.49   156.3 1948.82   166.1 1948.32     170 1948.81     176 1950.53
   179.3 1950.95   185.9 1950.97     206 1954.99   212.8  1957.4   219.7 1959.12
   223.1  1959.6   228.5 1959.49   240.1 1958.55   246.9 1958.75   265.4 1964.49
#Mann= 3 ,-1 , 0
       0      .1       0   125.2    .045       0     147      .1       0
Bank Sta=125.2,147
XS Rating Curve= 0 ,0
Exp/Cntr(USF)=0,0
Exp/Cntr=0.3,0.1

Type RM Length L Ch R = 1 ,6013    ,143.8,150.3,157.8
XS GIS Cut Line= 3
2022452.26177078254013.8218288872022395.83815965254101.495440021
2022301.76339096254137.011935204
#Sta/Elev= 30
       0 1962.29    11.6 1963.11    13.7 1963.03    16.4 1962.06    17.6 1961.28
    23.5  1954.8    30.6 1947.94    38.8 1941.55      41 1940.35    44.9 1939.47
    53.71938.576    56.6 1938.16    66.5 1938.61    72.2 1938.47    83.9 1936.01
    87.8 1936.43    92.4 1938.29    95.6  1940.5    99.5 1942.28   103.4 1943.09
     112 1942.68   119.5  1943.2     133 1947.05   150.6  1949.1   157.6 1951.82
   165.3 1956.34     173 1958.76   182.1 1963.13   199.7 1969.18   204.8    1972
#Mann= 3 ,-1 , 0
       0      .1       0    53.7    .045       0    66.5      .1       0
Bank Sta=53.7,66.5
XS Rating Curve= 0 ,0
Exp/Cntr(USF)=0,0
Exp/Cntr=0.3,0.1

Type RM Length L Ch R = 1 ,5862    ,150.8,152.2,150.7
XS GIS Cut Line= 2
2022360.24788189253975.7720603792022231.08121523254025.772060379
#Sta/Elev= 30
       0 1954.57     4.8 1953.01     8.3 1951.28    11.8 1949.12    18.9 1944.15
      24 1941.08    32.9 1936.28    36.4 1934.62    39.9 1933.26    43.5 1932.29
    49.4 1931.23      54    1930    61.1 1928.68    68.1 1928.15    73.6 1926.45
    75.1 1926.08    82.2 1925.59    85.7    1926    86.61926.355    89.2 1927.42
    92.5 1929.76    93.3 1930.53    97.5 1934.89   103.3 1940.51   107.7 1945.67
   119.1 1957.22   127.9 1966.85   131.4 1968.52   134.9 1968.35   138.5  1968.9
#Mann= 3 ,-1 , 0
       0      .1       0    73.6    .045       0    86.6      .1       0
Bank Sta=73.6,86.6
XS Rating Curve= 0 ,0
Exp/Cntr(USF)=0,0
Exp/Cntr=0.3,0.1

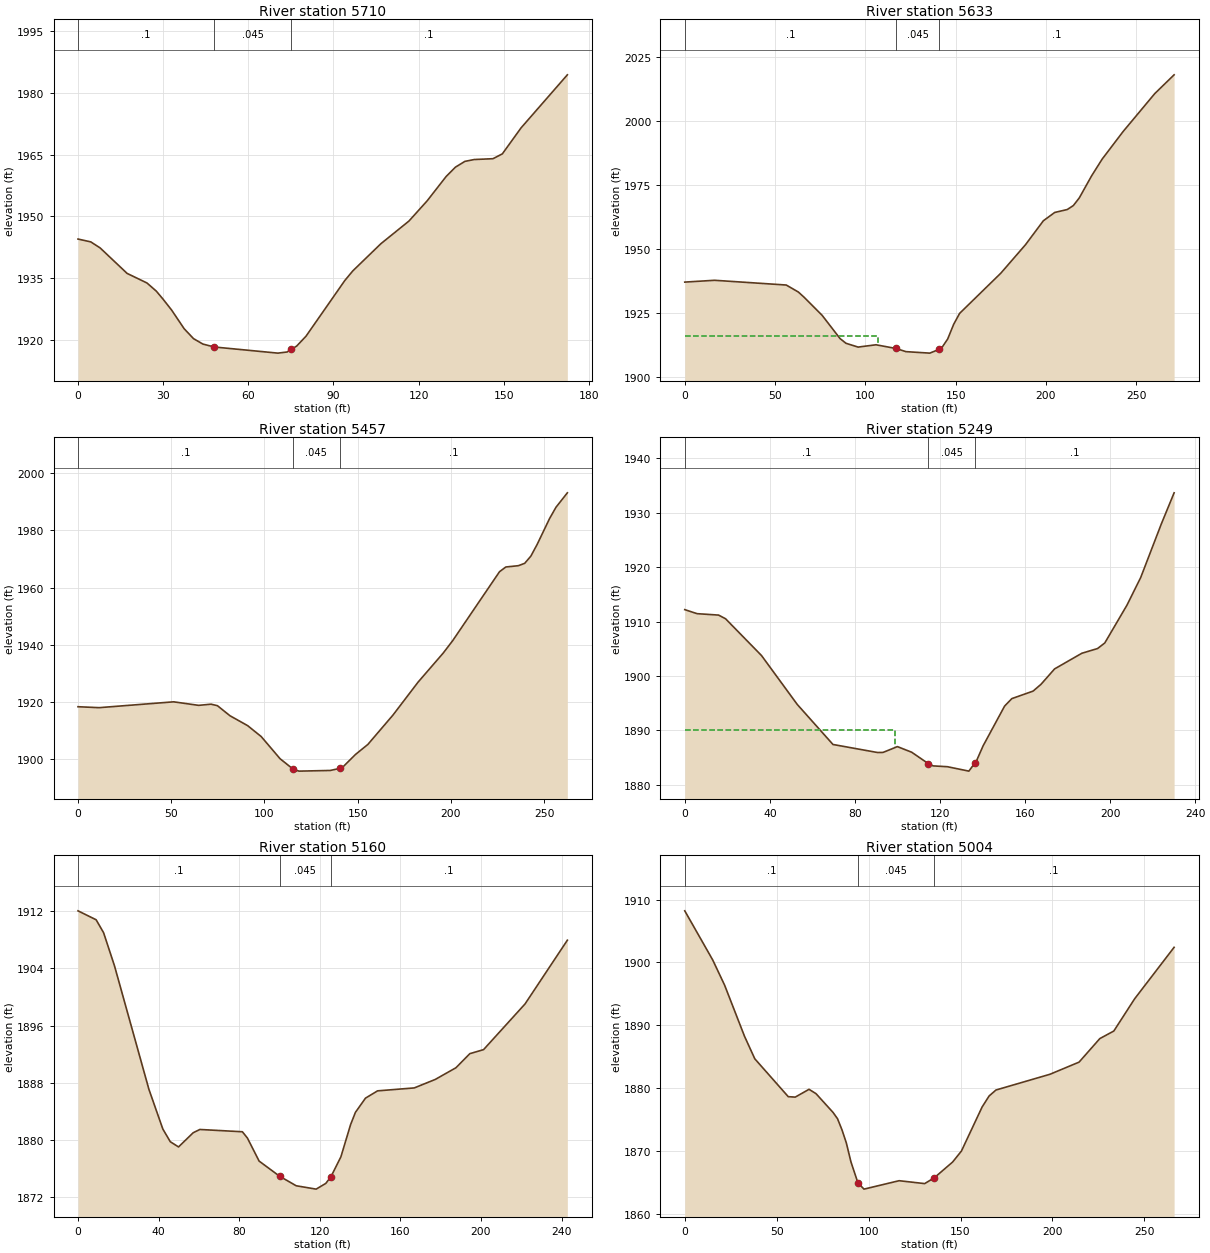
Type RM Length L Ch R = 1 ,5710    ,76.7,77.5,75
XS GIS Cut Line= 2
 2022373.3834779253859.249765202 2022201.7881227253876.036267341
#Sta/Elev= 30
       0 1944.48     4.5 1943.79     7.8 1942.32    17.3 1936.13    24.3  1933.8
    27.6 1931.81      30 1929.84      33  1927.2    37.4 1922.68    40.7 1920.27
      44 1918.95      48 1918.24    70.4 1916.75    73.7 1917.03      75 1917.65
      77 1918.44    80.3 1920.84      94  1934.4    96.8 1936.73   106.7 1943.34
   116.6 1948.86     123 1953.76   129.7 1959.69     133 1961.97   136.3 1963.36
   139.6 1963.81   146.2 1964.01   149.5 1965.19   156.1 1971.51   172.4  1984.4
#Mann= 3 ,-1 , 0
       0      .1       0      48    .045       0      75      .1       0
Bank Sta=48,75
XS Rating Curve= 0 ,0
Exp/Cntr(USF)=0,0
Exp/Cntr=0.3,0.1

Type RM Length L Ch R = 1 ,5633    ,177,176.1,173.8
XS GIS Cut Line= 2
2022421.37762493253775.0376755792022152.87117366253811.357700209
#Sta/Elev= 30
       0 1936.92    16.5 1937.63    56.2 1935.78    62.9 1933.05    66.2 1930.93
    76.1 1923.92      86 1914.86    89.3 1913.01      96 1911.53   105.9 1912.43
     1171910.981   122.5 1909.75   135.7 1909.17     1411910.675   142.3 1911.23
   145.6 1914.68   148.9 1920.39   152.2 1924.69     175 1940.38   188.7 1951.53
   198.6 1960.89   204.9 1964.14   211.8 1965.27   215.2 1966.83   218.5 1969.83
   225.3 1978.43   231.2 1985.02   242.8 1995.79   260.3 2010.58     271 2017.91
#Mann= 3 ,-1 , 0
       0      .1       0     117    .045       0     141      .1       0
#XS Ineff= 2 , 0
             107    1916
Permanent Ineff=
       F       F
Bank Sta=117,141
XS Rating Curve= 0 ,0
Exp/Cntr=0.3,0.1

Type RM Length L Ch R = 1 ,5457    ,196.1,207.2,211.4
XS GIS Cut Line= 2
2022425.52244027253592.6658004872022169.41979397253650.076014611
#Sta/Elev= 30
       0 1918.39    11.3 1918.06    51.3  1920.1    64.7 1918.87    71.4 1919.28
    74.8 1918.75    81.5 1915.25      91 1911.78    98.3 1907.95   108.4 1900.22
   115.2 1896.68   118.5 1895.89   135.3 1896.12   140.51896.855   142.1 1897.34
   148.8 1901.68   155.5 1905.22     169 1915.51   182.4 1926.96   195.9 1937.13
     201 1941.48   226.1 1965.55   229.5 1967.21   236.2 1967.66   239.6 1968.48
   242.9 1970.98   246.3 1975.09     253 1984.18   256.4 1988.07   262.5 1993.12
#Mann= 3 ,-1 , 0
       0      .1       0   115.2    .045       0   140.5      .1       0
Bank Sta=115.2,140.5
XS Rating Curve= 0 ,0
Exp/Cntr=0.3,0.1

Type RM Length L Ch R = 1 ,5249    ,84.1,89.7,92.7
XS GIS Cut Line= 3
2022407.38887315 253455.368792252022215.53809022253412.194463126
2022183.05074271253420.137861835
#Sta/Elev= 30
       0 1912.18     5.8 1911.44    15.9 1911.18    19.2  1910.5    36.1 1903.75
    52.9 1894.78    69.7 1887.43    90.6 1885.96    93.2 1885.97     100 1887.04
   106.7 1886.01   114.61883.896   116.8  1883.5   123.5 1883.35   133.6 1882.54
   136.31883.967   137.3 1884.53   140.3 1887.19   150.4 1894.48   153.8 1895.85
   163.8 1897.23   167.5 1898.47   173.9  1901.3   186.7 1904.17   194.1 1905.04
   197.5 1906.06   207.9 1912.98   214.4 1918.08   224.1 1927.92   230.1 1933.62
#Mann= 3 ,-1 , 0
       0      .1       0   114.6    .045       0   136.3      .1       0
#XS Ineff= 2 , 0
              99    1890
Permanent Ineff=
       F       F
Bank Sta=114.6,136.3
XS Rating Curve= 0 ,0
Exp/Cntr=0.3,0.1

Type RM Length L Ch R = 1 ,5160    ,176.8,155.2,133.2
XS GIS Cut Line= 3
2022413.08799424253395.2689697772022264.13033471 253320.05231112
2022191.34037339253341.904472236
#Sta/Elev= 30
       0 1912.04       9 1910.79    12.7 1908.98    18.1 1904.36    35.2 1887.08
    42.1 1881.54    45.8 1879.76    49.9 1879.03    57.2 1881.02    60.5 1881.47
    81.6 1881.15    84.1 1880.27    89.9 1877.05   100.11874.927   108.3  1873.6
   118.2 1873.13     123 1873.93   125.6 1874.89   130.5 1877.65   135.3 1882.15
   137.7 1883.86   142.7 1885.85   148.7 1886.87   166.9 1887.28   177.3 1888.46
   187.6  1890.1   194.5 1892.07   201.3 1892.63   221.9 1899.02   242.9 1907.93
#Mann= 3 ,-1 , 0
       0      .1       0   100.1    .045       0   125.6      .1       0
Bank Sta=100.1,125.6
XS Rating Curve= 0 ,0
Exp/Cntr(USF)=0,0
Exp/Cntr=0.3,0.1

Type RM Length L Ch R = 1 ,5004    ,218.3,215.7,212.2
XS GIS Cut Line= 3
 2022423.4500326253163.6774124872022380.96906879253165.181084156
2022186.15935421 253275.06932483
#Sta/Elev= 30
       0 1908.22    15.2  1900.4    21.7 1896.37    32.5 1888.25    38.1 1884.66
    56.3 1878.63    60.1 1878.56    67.6  1879.8    71.4 1879.11    80.7 1876.11
    83.1 1875.12    85.5 1873.37    87.9 1871.26    90.4 1868.25    94.2 1864.91
    97.5 1863.91   116.6 1865.25   130.5 1864.79   135.71865.707   145.7 1868.22
   150.5 1869.97   161.8 1877.01   165.6 1878.75   169.3 1879.69   198.7  1882.2
   214.5 1884.13   225.8 1887.88   233.4 1889.08   244.7  1894.2   266.2 1902.41
#Mann= 3 ,-1 , 0
       0      .1       0    94.2    .045       0   135.7      .1       0
Bank Sta=94.2,135.7
XS Rating Curve= 0 ,0
Exp/Cntr(USF)=0,0
Exp/Cntr=0.3,0.1

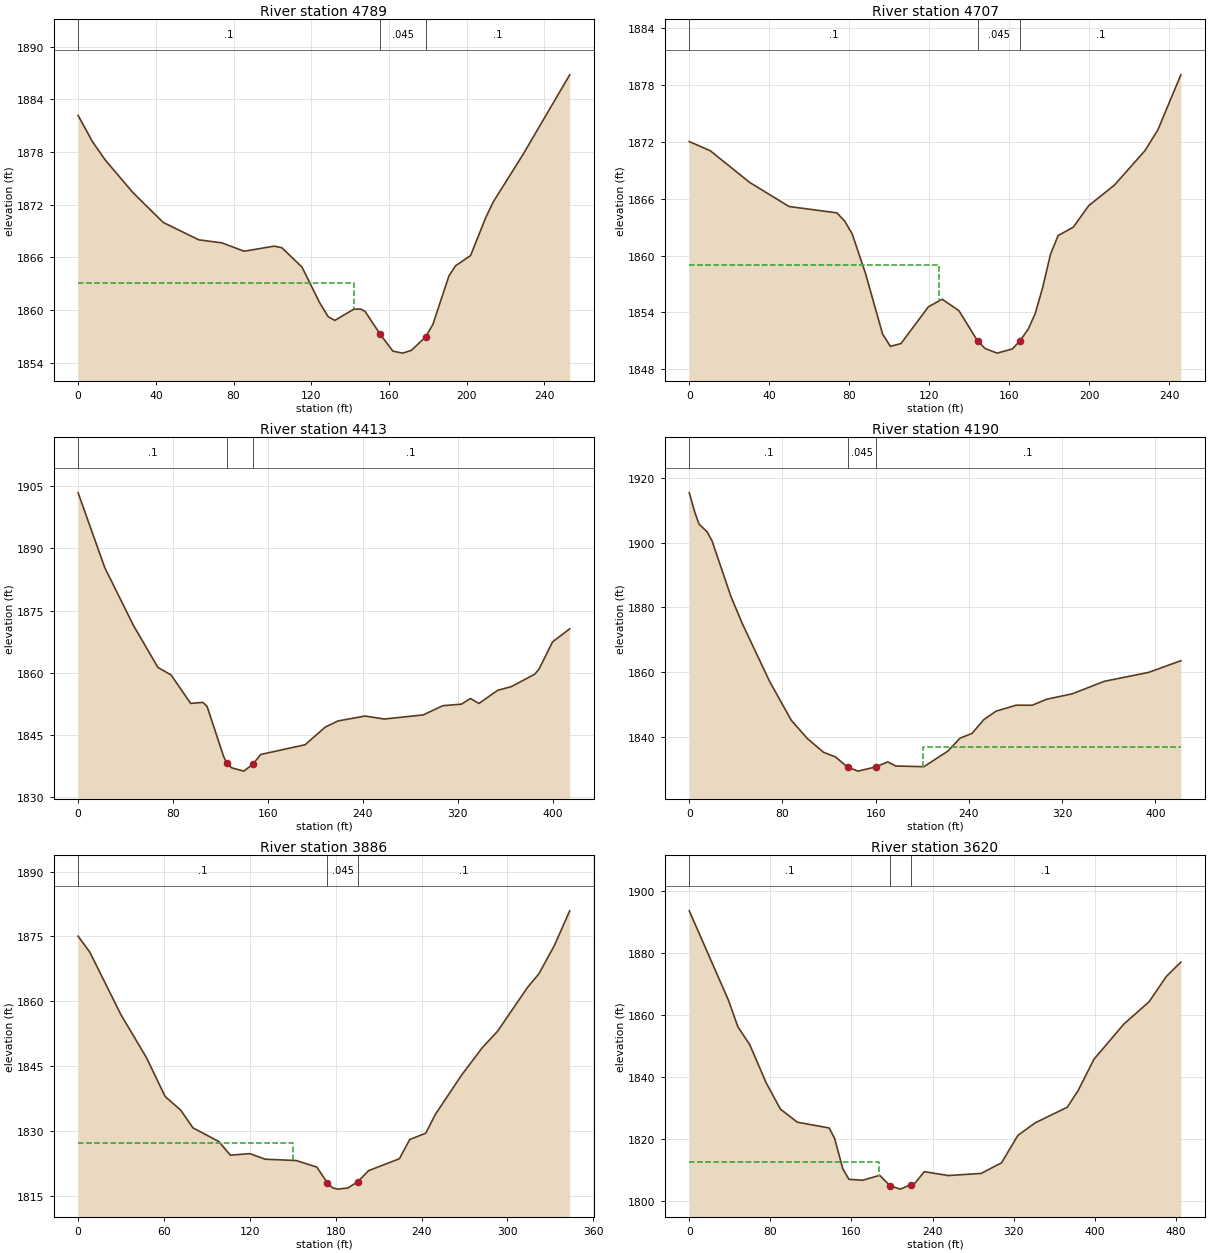
Type RM Length L Ch R = 1 ,4789    ,81.1,81.4,82.5
XS GIS Cut Line= 3
2022320.34775094252962.1357664342022292.54493173 252967.14245694
2022102.74494544 253087.51643056
#Sta/Elev= 30
       0 1882.18     7.3 1879.22      14 1877.09    28.3 1873.36    43.8 1869.98
    62.1    1868      74 1867.65    85.4  1866.7     101 1867.28   104.9 1867.09
   115.2  1864.9   124.3 1860.83   128.7 1859.23   132.1 1858.81   141.8 1860.08
   145.3 1860.11   147.6 1859.86   155.51857.223     162 1855.31     167 1855.08
   171.5 1855.39   178.9 1856.94   182.6 1858.36   190.8 1863.86   194.2 1865.03
     202 1866.21   209.8 1870.54   213.6  1872.3   229.2 1877.81     253 1886.81
#Mann= 3 ,-1 , 0
       0      .1       0   155.5    .045       0   178.9      .1       0
#XS Ineff= 2 , 0
             142 1863.07
Permanent Ineff=
       F       F
Bank Sta=155.5,178.9
XS Rating Curve= 0 ,0
Exp/Cntr(USF)=0,0
Exp/Cntr=0.3,0.1

Type RM Length L Ch R = 1 ,4707    ,279,294.7,305.6
XS GIS Cut Line= 3
2022290.81594162 252921.723816842022224.12769613252919.376177175
2022070.10452461253010.837346714
#Sta/Elev= 30
       0 1872.01    10.5 1871.05    30.2 1867.71    49.9 1865.17    73.8  1864.5
    77.7 1863.65    81.5 1862.28    88.2 1858.09    96.7 1851.73   100.6 1850.42
   105.9 1850.72   119.6 1854.59   126.5 1855.39   134.9 1854.19   144.21851.007
     148  1850.2     154 1849.71   161.6 1850.15   165.5 1851.02   169.6 1852.26
   173.1  1853.9   176.8 1856.64   180.7 1860.13   184.5  1862.1   192.1 1862.99
   199.8 1865.25   212.7 1867.43     228 1871.07   234.4 1873.24   245.9 1879.05
#Mann= 3 ,-1 , 0
       0      .1       0   144.2    .045       0   165.5      .1       0
#XS Ineff= 2 , 0
             125 1859.05
Permanent Ineff=
       F       F
Bank Sta=144.2,165.5
XS Rating Curve= 0 ,0
Exp/Cntr(USF)=0,0
Exp/Cntr=0.3,0.1

Type RM Length L Ch R = 1 ,4413    ,220,222.2,220.8
XS GIS Cut Line= 3
2022331.29657192252747.5498292132022111.77466426 252676.92182437
2021945.42642503252755.229752732
#Sta/Elev= 30
       0 1903.38    22.5 1885.33    46.6 1871.44    67.3 1861.28    78.4 1859.46
    94.9 1852.61   105.2 1852.85   108.7 1851.92   122.7  1839.8   125.3 1838.21
   129.3  1837.1   139.7 1836.28   147.21837.919     154  1840.3   191.4 1842.64
   208.3 1846.88     219 1848.37     242 1849.56   258.2 1848.84   290.9 1849.83
   307.6 1852.06   323.3 1852.43   330.8 1853.79     338  1852.6   353.8 1855.77
   365.3 1856.66     385 1859.64   388.8 1860.96     400 1867.43   414.5 1870.59
#Mann= 3 ,-1 , 0
       0      .1       0   125.3    .045       0   147.2      .1       0
Bank Sta=125.3,147.2
XS Rating Curve= 0 ,0
Exp/Cntr(USF)=0,0
Exp/Cntr=0.3,0.1

Type RM Length L Ch R = 1 ,4190    ,302.4,304.9,306.1
XS GIS Cut Line= 2
2022416.27823899252552.4319216052022014.48491706252423.939640984
#Sta/Elev= 30
       0 1915.48     4.9 1909.29     8.4  1905.8    15.3 1903.41    19.6 1900.54
    35.9 1883.25    45.7 1874.84    69.1 1856.97    87.6 1845.02   101.4 1839.37
   115.2 1835.14   125.5 1833.69   135.8 1830.55   144.8  1829.3   159.9 1830.59
   170.3 1832.16   177.2 1830.89   201.3 1830.67   221.9 1835.49   232.3  1839.5
   242.6 1840.97   252.9 1845.31   263.3 1847.87   280.4 1849.72   294.3  1849.7
   306.6 1851.55   328.7 1853.25   356.1 1857.11   394.2 1859.88   421.8 1863.49
#Mann= 3 ,-1 , 0
       0      .1       0   135.8    .045       0   159.9      .1       0
#XS Ineff= 2 , 0
                          200.28         1836.83
Permanent Ineff=
       F       F
Bank Sta=135.8,159.9
XS Rating Curve= 0 ,0
Exp/Cntr(USF)=0,0
Exp/Cntr=0.3,0.1

Type RM Length L Ch R = 1 ,3886    ,251.5,265.2,278.7
XS GIS Cut Line= 2
2022484.66593228252298.583999508 2022172.0449345252156.164773652
#Sta/Elev= 30
       0 1875.06     8.2 1871.36    29.8 1856.98    47.9 1846.88    60.8 1837.99
    71.7 1834.81    80.3 1830.71    98.3 1827.57   106.4  1824.4     120 1824.76
   130.8 1823.47   152.4 1823.16   166.8 1821.65     174 1818.07   177.7 1816.88
   181.3 1816.55   188.5 1816.81   195.4 1818.27     203 1820.83   224.5 1823.58
   231.7 1828.02   242.9 1829.49   249.8 1833.93   267.8 1842.86   282.4 1849.27
     293 1853.03   314.1 1863.25   321.9 1866.33   332.7 1872.84   343.5 1880.93
#Mann= 3 ,-1 , 0
       0      .1       0     174    .045       0   195.4      .1       0
#XS Ineff= 2 , 0
          150.25 1827.19
Permanent Ineff=
       F       F
Bank Sta=174,195.4
XS Rating Curve= 0 ,0
Exp/Cntr=0.3,0.1

Type RM Length L Ch R = 1 ,3620    ,282.3,276.5,264
XS GIS Cut Line= 4
2022555.14354583252207.1818259552022482.22401265252147.919186319
2022410.99026668251866.9524258072022335.29513396251799.798653878
#Sta/Elev= 30
       0  1893.5    38.7 1864.72      48 1856.17    59.7 1850.41      76 1838.07
      90 1829.67   106.7 1825.47     138 1823.63   143.4 1820.28   151.5  1810.5
   157.5 1807.11     171 1806.79   187.9 1808.38   198.1 1805.02   208.2 1803.94
   218.4 1805.34   221.8 1805.53   231.9 1809.56   255.6 1808.31     288    1809
   308.1 1812.41   324.3 1821.26   341.4 1825.29   372.9 1830.29   383.7 1835.68
   399.3 1845.75   428.9 1857.09   453.7 1864.24   470.7 1872.39     485 1876.99
#Mann= 3 ,-1 , 0
       0      .1       0   198.1    .045       0   218.4      .1       0
#XS Ineff= 2 , 0
          187.02  1812.8
Permanent Ineff=
       F       F
Bank Sta=198.1,218.4
XS Rating Curve= 0 ,0
Exp/Cntr=0.3,0.1

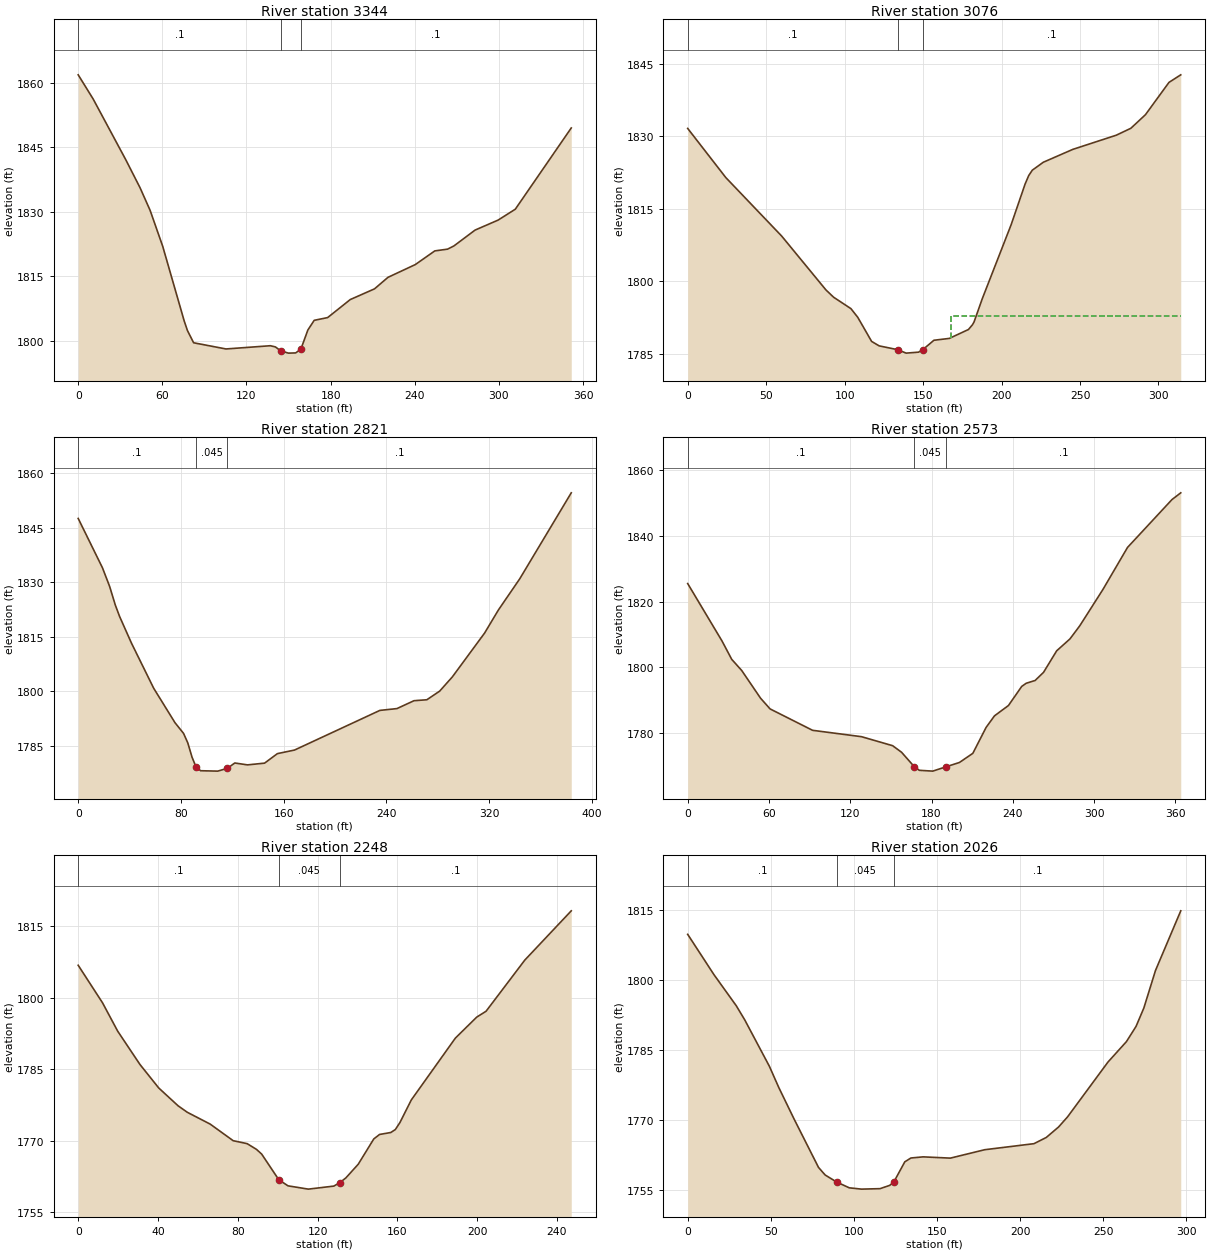
Type RM Length L Ch R = 1 ,3344    ,267,267.5,266.9
XS GIS Cut Line= 2
2022711.33458709251946.0027453442022455.70973252251704.654810846
#Sta/Elev= 30
       0 1861.81    10.7 1856.17    33.9 1842.08    44.1 1835.55    51.3 1830.27
    60.3 1821.89    75.6 1804.55    77.9 1802.33    82.3 1799.48   105.4 1798.04
     137 1798.79   140.6 1798.52   144.4 1797.61   149.9 1797.07   155.1 1797.12
   158.8    1798   163.8 1802.46   168.3  1804.7   177.9 1805.34     194 1809.53
   211.3 1812.02   220.9  1814.7   240.4 1817.67   254.3 1820.85   263.4 1821.26
   267.9    1822     283 1825.69   299.4 1828.01   311.7 1830.55   351.6 1849.45
#Mann= 3 ,-1 , 0
       0      .1       0   144.4    .045       0   158.8      .1       0
Bank Sta=144.4,158.8
XS Rating Curve= 0 ,0
Exp/Cntr(USF)=0,0
Exp/Cntr=0.3,0.1

Type RM Length L Ch R = 1 ,3076    ,263.7,255.7,243.8
XS GIS Cut Line= 2
2022859.72337227251721.9777325792022625.82704083251512.164920807
#Sta/Elev= 30
       0 1831.63    24.3 1821.47    59.9 1809.38    88.1 1798.25      93 1796.74
     104 1794.39   108.4 1792.58   117.2 1787.61     122 1786.69   133.7 1785.91
   139.2 1785.19   147.1 1785.39   149.9 1785.93   156.9 1787.85   166.7 1788.23
   178.9 1790.07   181.5 1791.07   182.5 1791.65   187.7 1796.42   206.1 1811.72
     215 1820.13   217.3 1821.88   219.6    1823   226.6 1824.64   245.4  1827.3
   273.1 1830.23   282.4 1831.66   291.7 1834.47   306.7 1841.15   314.2 1842.71
#Mann= 3 ,-1 , 0
       0      .1       0   133.7    .045       0   149.9      .1       0
#XS Ineff= 2 , 0
                           167.8         1792.93
Permanent Ineff=
       F       F
Bank Sta=133.7,149.9
XS Rating Curve= 0 ,0
Exp/Cntr=0.3,0.1

Type RM Length L Ch R = 1 ,2821    ,248.9,247.3,245
XS GIS Cut Line= 3
2023020.76478366 251456.114603372022730.37048051251408.238756082
2022648.78808012251370.846822568
#Sta/Elev= 30
       0 1847.61    18.9 1834.02    24.5 1828.88    28.9 1823.78    32.2 1820.66
    41.6  1813.2    58.8 1800.86    75.4 1791.37    82.1 1788.41    85.4 1785.78
    88.7 1781.85    91.91779.099    95.4 1778.14   108.7 1778.03   116.21778.798
     122 1780.27   131.9 1779.75   145.2 1780.23   155.2 1782.85   168.5 1783.83
     235 1794.75   248.3 1795.25   261.6 1797.42   271.6 1797.68   281.6 1800.06
   291.5 1803.99   316.6 1816.05   327.4 1822.43     344    1831   384.1 1854.66
#Mann= 3 ,-1 , 0
       0      .1       0    91.9    .045       0   116.2      .1       0
Bank Sta=91.9,116.2
XS Rating Curve= 0 ,0
Exp/Cntr(USF)=0,0
Exp/Cntr=0.3,0.1

Type RM Length L Ch R = 1 ,2573    ,314.7,325.8,339.5
XS GIS Cut Line= 4
2023100.60910707 251232.375015812023049.90154872251198.843928404
 2022852.7440811251188.6461283552022758.92432065251139.696688119
#Sta/Elev= 30
       0 1825.44    25.4 1807.99    32.5 1802.47    39.9 1799.08    53.8 1790.69
    60.8 1787.45    92.2 1780.96   128.3 1779.03   151.3  1776.3   157.9  1774.3
   167.21769.969     171 1768.84   180.9 1768.59   190.71769.903   200.6 1771.21
   210.5 1773.98   220.3 1781.84   226.5 1785.35   236.8 1788.48   246.6 1794.27
   249.9 1795.22   256.5 1796.07   262.7 1798.53   272.4 1805.06   282.2 1808.66
   289.5 1812.67   306.5 1823.62   324.7 1836.39   357.5 1850.89     364 1852.94
#Mann= 3 ,-1 , 0
       0      .1       0   167.2    .045       0   190.7      .1       0
Bank Sta=167.2,190.7
XS Rating Curve= 0 ,0
Exp/Cntr(USF)=0,0
Exp/Cntr=0.3,0.1

Type RM Length L Ch R = 1 ,2248    ,213.9,221.6,227.4
XS GIS Cut Line= 2
2023211.84904346251018.7827725052023035.17110845250845.881800473
#Sta/Elev= 30
       0 1806.84    12.2 1798.95    19.8 1792.99      31 1785.97    40.4 1781.04
    50.1  1777.3    54.7 1775.94    66.2 1773.45    77.7 1769.97    84.7 1769.35
    89.4 1768.14      92 1767.15   100.6 1761.75   105.2 1760.48   115.4 1759.79
   128.2 1760.43   131.21761.168   134.2 1762.15   140.4 1765.02   148.2 1770.34
   151.1 1771.28   156.7 1771.69     159 1772.31   161.3 1773.78     167 1778.53
   189.1 1791.53   199.8 1795.94   204.5 1797.18   223.9 1807.92   247.2 1818.28
#Mann= 3 ,-1 , 0
       0      .1       0   100.6    .045       0   131.2      .1       0
Bank Sta=100.6,131.2
XS Rating Curve= 0 ,0
Exp/Cntr=0.3,0.1

Type RM Length L Ch R = 1 ,2026    ,412.8,396.9,381.5
XS GIS Cut Line= 3
2023349.07869845 250896.241306892023226.66341624250662.439645815
2023199.67882941 250644.02411225
#Sta/Elev= 30
       0 1809.71    15.8 1801.09    29.2 1794.45    34.3 1791.43    49.1 1781.52
    54.8 1776.95    63.9 1770.28    78.7 1759.86    82.7 1758.24    89.71756.717
    97.2  1755.5   104.5 1755.22   115.7 1755.32   121.5 1756.02     124 1756.75
   130.6 1761.06   134.3 1761.88   141.7 1762.12     158 1761.85   178.7 1763.65
   208.3 1764.94   215.7 1766.27   223.1 1768.51   228.5 1770.67   252.8 1782.39
   263.9 1786.76   269.7 1790.02   274.4 1793.96   281.4 1801.98   296.6 1814.74
#Mann= 3 ,-1 , 0
       0      .1       0    89.7    .045       0     124      .1       0
Bank Sta=89.7,124
XS Rating Curve= 0 ,0
Exp/Cntr=0.3,0.1

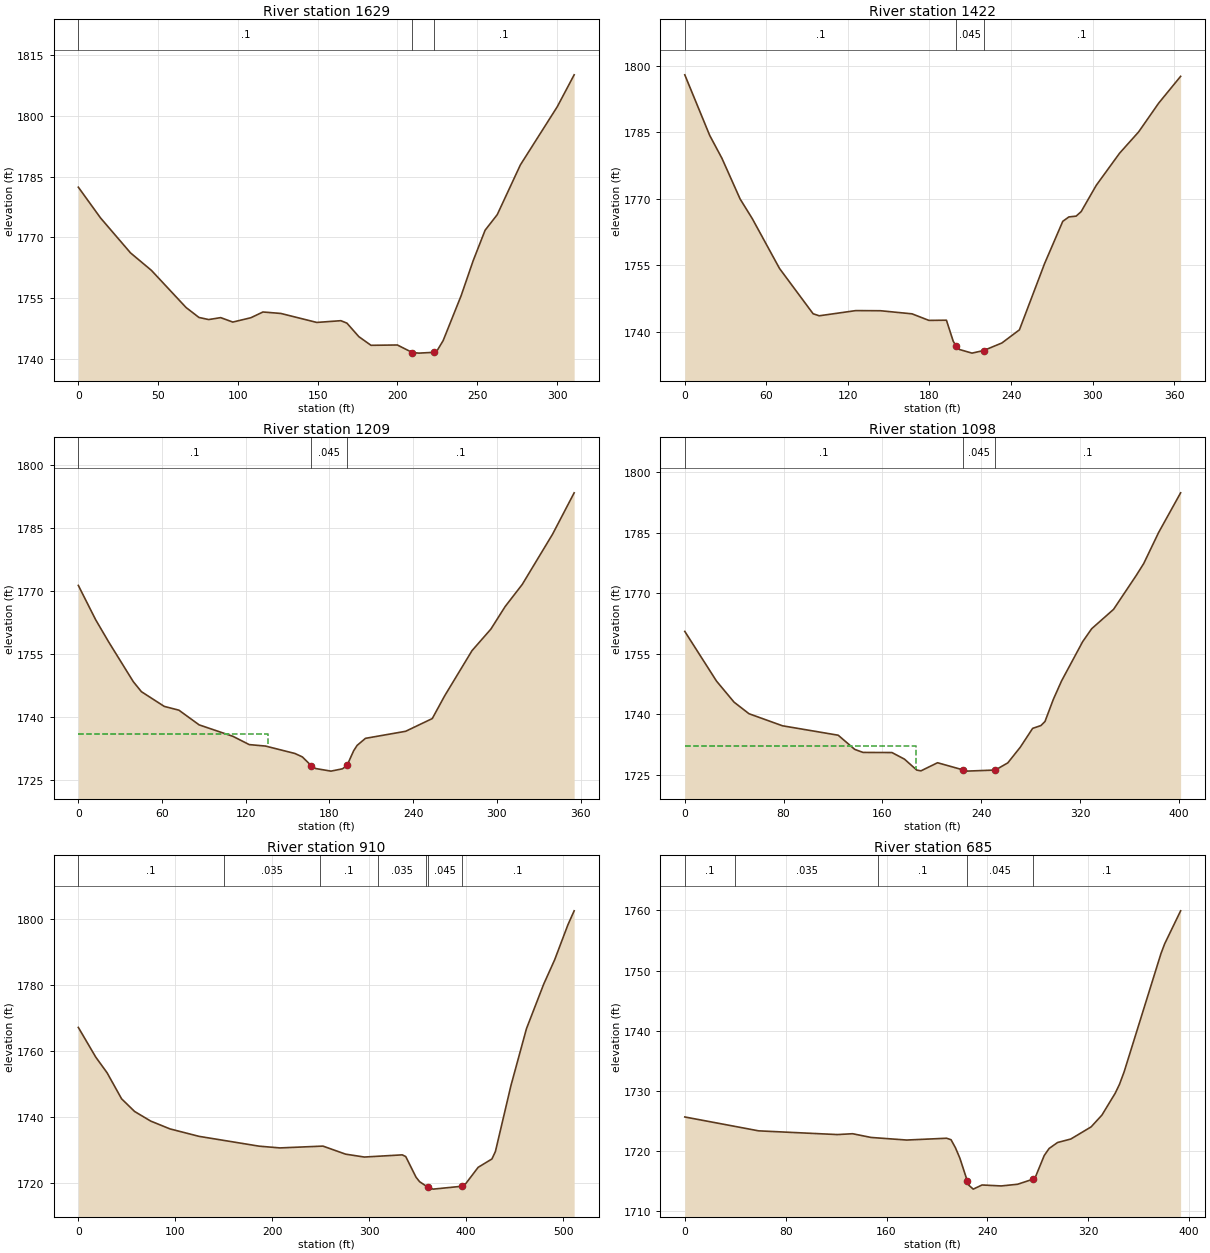
Type RM Length L Ch R = 1 ,1629    ,202.9,206.9,208.2
XS GIS Cut Line= 2
2023611.35665773250555.2436912332023340.68544738   250402.718144
#Sta/Elev= 30
       0 1782.37    13.9 1774.78    32.7 1766.14    45.8 1761.82    67.5 1752.65
    75.6 1750.19    81.7 1749.67    89.2 1750.15    96.8 1749.05   108.1 1750.12
   115.7 1751.54   126.9 1751.18   149.4 1748.96   164.5 1749.39   168.3 1748.79
   175.8 1745.44   183.4 1743.31   199.9 1743.39   209.3 1741.53   213.5 1741.38
   222.61741.576   224.8 1741.98   228.6 1744.47   239.9 1755.59   247.4 1764.19
   254.9 1771.74   262.5 1775.58     277 1787.87   300.1 1802.23   310.7 1810.12
#Mann= 3 ,-1 , 0
       0      .1       0   209.3    .045       0   222.6      .1       0
Bank Sta=209.3,222.6
XS Rating Curve= 0 ,0
Exp/Cntr(USF)=0,0
Exp/Cntr=0.3,0.1

Type RM Length L Ch R = 1 ,1422    ,213.2,213.6,210.9
XS GIS Cut Line= 3
2023707.78352097250445.7730571612023492.91629359250246.013681711
2023425.87694574250221.423920897
#Sta/Elev= 30
       0 1798.02    18.3 1784.36    27.3 1779.19    40.7 1769.99    49.7 1765.53
    69.7  1754.3    94.4 1744.08    98.9 1743.62   125.8 1744.79     144 1744.76
   167.2 1744.06   179.6 1742.58   192.5 1742.62   197.5 1737.87   199.6 1736.81
     202 1736.02   211.3 1735.19   219.9 1735.78   233.3 1737.48   246.2 1740.45
   264.7  1755.4   278.1 1764.95   282.6 1765.94   287.9 1766.12   291.6 1767.13
   302.7 1773.06   319.9 1780.33   333.9 1785.13   348.7 1791.65   364.8 1797.68
#Mann= 3 ,-1 , 0
       0      .1       0   199.6    .045       0   219.9      .1       0
Bank Sta=199.6,219.9
XS Rating Curve= 0 ,0
Exp/Cntr(USF)=0,0
Exp/Cntr=0.3,0.1

Type RM Length L Ch R = 1 ,1209    ,118.3,110.2,102.6
XS GIS Cut Line= 3
2023796.26398564250230.2042235932023577.22772951250064.787570881
2023498.64803417250045.423249452
#Sta/Elev= 30
       0 1771.39    12.4 1763.23    21.8  1757.9    39.4 1748.46    45.2 1746.08
    61.6 1742.57    72.1 1741.67    86.6 1738.17   110.8 1735.44   122.5 1733.47
   134.2 1733.12   155.3 1731.35   160.6 1730.53     167 1728.44   170.1 1727.77
   181.1 1727.15   189.3  1727.7   192.61728.492   197.3 1731.97   199.8 1733.27
   205.8 1734.96   234.6 1736.64   253.7 1739.67   262.6  1745.1   282.2 1755.86
   295.7 1760.98   305.9 1766.34   318.2 1771.63   339.9 1783.58   355.4 1793.45
#Mann= 3 ,-1 , 0
       0      .1       0     167    .045       0   192.6      .1       0
#XS Ineff= 2 , 0
             136    1736
Permanent Ineff=
       F       F
Bank Sta=167,192.6
XS Rating Curve= 0 ,0
Exp/Cntr(USF)=0,0
Exp/Cntr=0.3,0.1

Type RM Length L Ch R = 1 ,1098    ,176.6,188.6,188.1
XS GIS Cut Line= 4
2023837.07563517250148.1332349122023790.98650104250038.034368618
 2023598.3426003 249998.536723552023519.53555512249965.676632874
#Sta/Elev= 30
       0 1760.51    25.7 1748.17    39.9 1742.95      52 1740.08    79.1 1737.09
   124.2 1734.75   137.6 1731.23   144.3 1730.48   167.7 1730.45   177.8 1728.82
   187.8  1726.1   191.2 1725.91   204.6 1727.92   224.91726.178     228 1725.84
   251.41726.109   261.5 1727.89   271.6 1731.78   281.6 1736.45   288.3 1737.15
   291.6 1738.16   298.3 1743.61     305 1748.22   322.1 1757.97   329.4 1761.18
   347.1 1765.98   365.4 1774.37   371.5 1777.34   383.6 1785.06   401.4  1794.9
#Mann= 3 ,-1 , 0
       0      .1       0   224.9    .045       0   251.4      .1       0
#XS Ineff= 2 , 0
             187    1732
Permanent Ineff=
       F       F
Bank Sta=224.9,251.4
XS Rating Curve= 0 ,0
Exp/Cntr(USF)=0,0
Exp/Cntr=0.3,0.1

Type RM Length L Ch R = 1 ,910     ,225.4,224.5,223.8
XS GIS Cut Line= 3
2023884.68759272250109.3982849662023851.94895808249913.266645673
2023563.71933041249792.438715272
#Sta/Elev= 30
       0 1767.05      18 1758.05    29.7  1753.3    44.6 1745.45      58 1741.62
    74.6 1738.71    94.5 1736.34   124.5 1734.08   186.5 1731.11     208 1730.58
   252.3 1731.13   275.7 1728.69     295 1727.82   334.1 1728.48   337.7 1727.96
   348.3 1721.73   351.9 1720.38   360.71718.642     366 1718.11   395.71718.981
   399.5 1719.74   412.4 1724.71   426.6 1727.24   430.2 1729.51   446.2 1749.45
   462.2 1766.66     480 1780.15   491.3 1787.52   504.9 1798.06   511.4 1802.33
#Mann= 7 ,-1 , 0
       0      .1       0     150    .035       0  248.85      .1       0
  308.85    .035       0  358.85      .1       0   360.7    .045       0
   395.7      .1       0
Bank Sta=360.7,395.7
XS Rating Curve= 0 ,0
Exp/Cntr(USF)=0,0
Exp/Cntr=0.3,0.1

Type RM Length L Ch R = 1 ,685     ,246.1,245.5,245.8
XS GIS Cut Line= 3
2023889.41006783249812.1779817382023881.97249436249679.244723701
2023639.49664547249585.061717746
#Sta/Elev= 30
       0 1725.63    58.6 1723.32     121  1722.7   133.1 1722.84   147.8 1722.22
     176 1721.79   207.7 1722.09   211.2 1721.84   214.7  1720.5   218.2 1718.77
   224.11714.977   225.3 1714.27   228.8 1713.62   235.8 1714.31     251 1714.15
     264 1714.43   276.41715.289   278.1 1715.62   285.1 1719.21     289 1720.39
   295.7 1721.38   306.2 1721.96   322.3 1723.98   330.9 1725.95   341.4 1729.58
   344.8 1731.06   348.5 1733.15   377.7 1752.82   380.6 1754.43   393.3 1759.94
#Mann= 5 ,-1 , 0
       0      .1       0      40    .035       0  153.14      .1       0
   224.1    .045       0   276.4      .1       0
Bank Sta=224.1,276.4
XS Rating Curve= 0 ,0
Exp/Cntr(USF)=0,0
Exp/Cntr=0.3,0.1