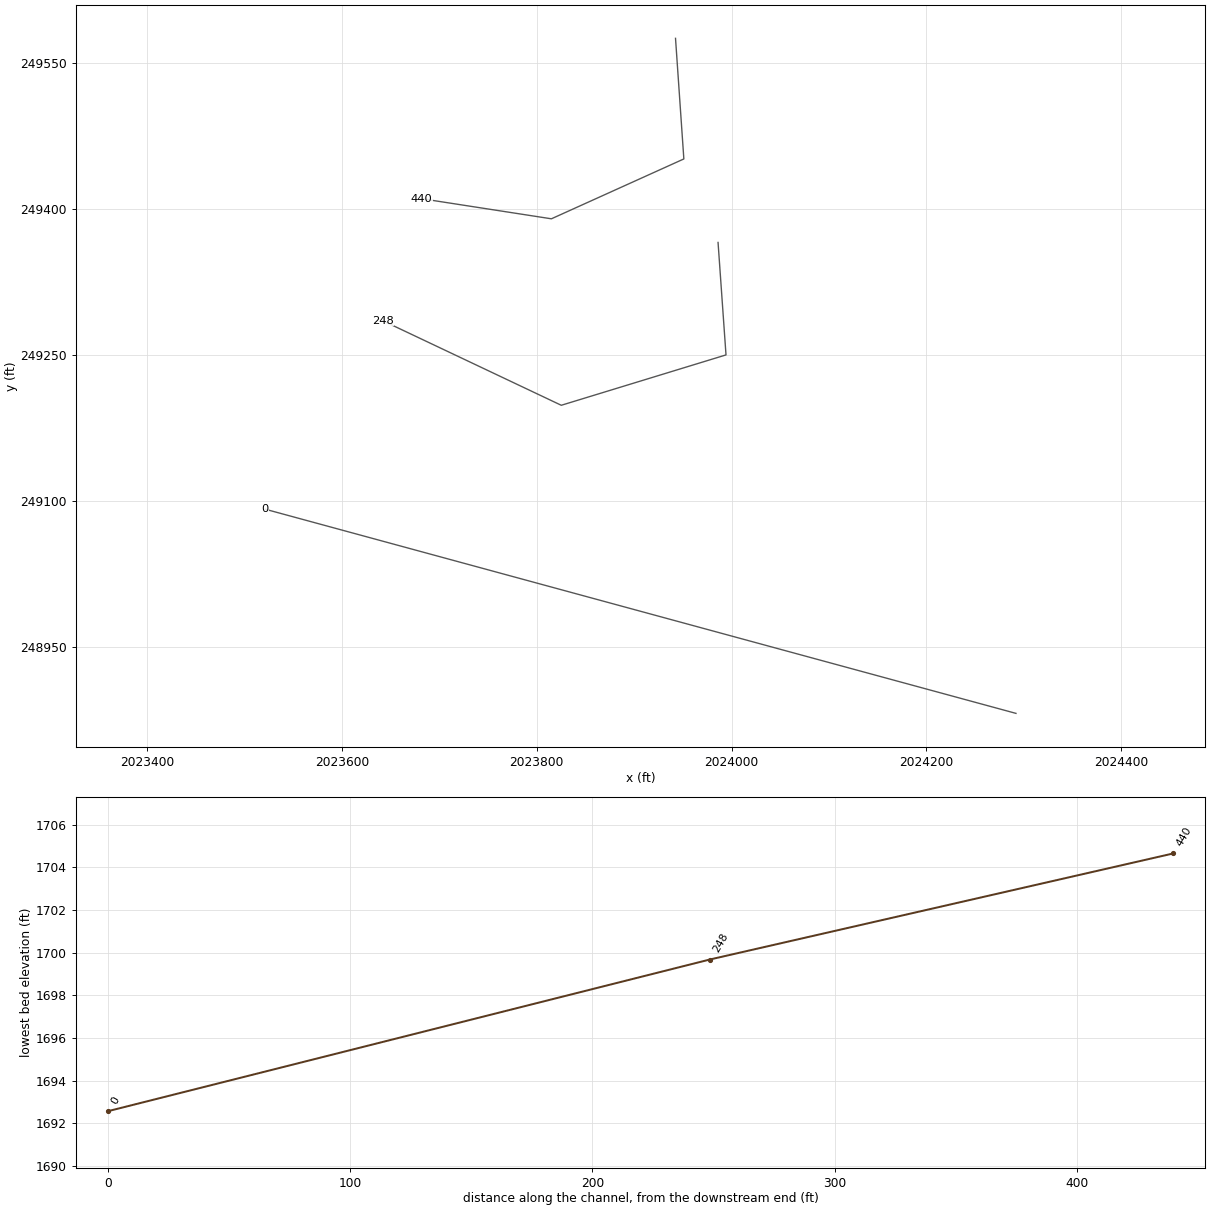
HEC-RAS study BIGCK_T1.prj: BIGCK_T1

--- BIGCK_T1.g01 (geometry) --- (continued)

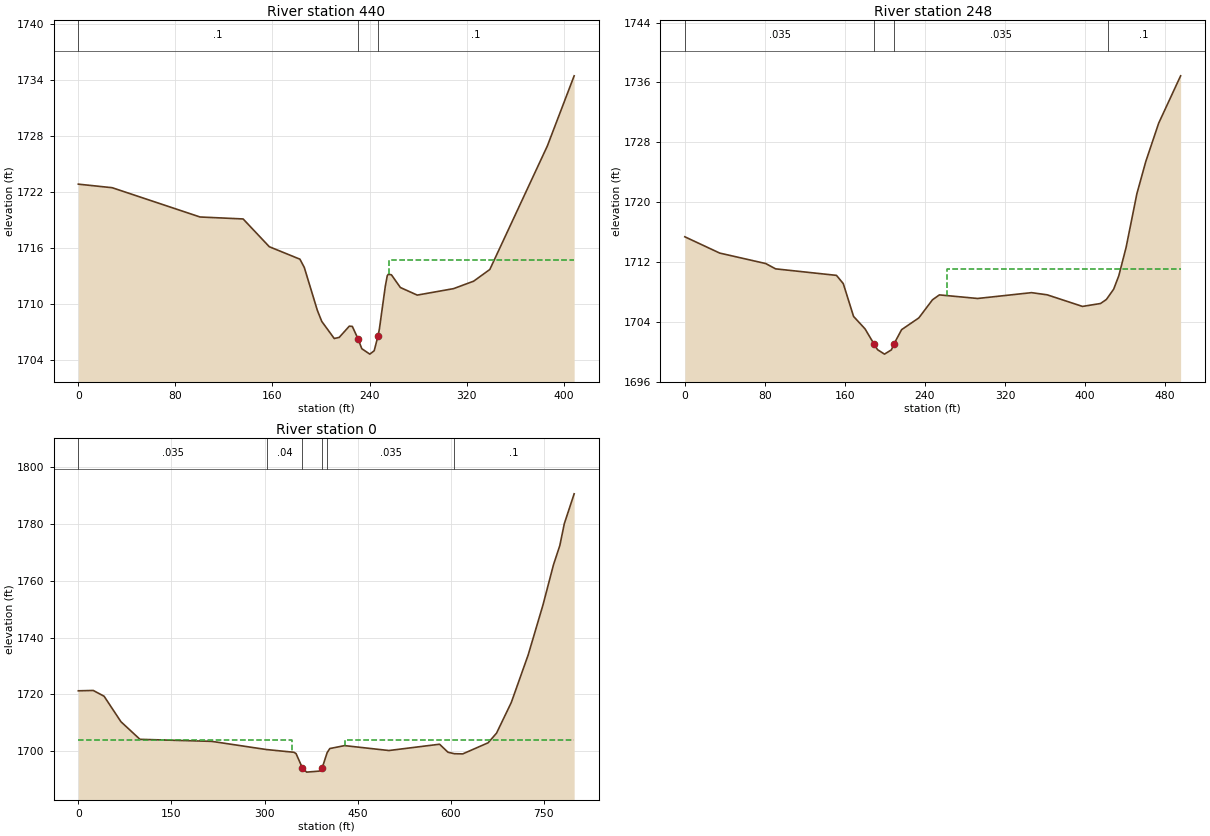
Type RM Length L Ch R = 1 ,440     ,193.1,191.3,189.5
XS GIS Cut Line= 4
2023942.49901019249574.8546691352023951.05275008249450.992045444
2023815.02781028249389.5201984462023681.44241081249410.204863717
#Sta/Elev= 30
       0 1722.83    27.9 1722.45   100.3 1719.32   135.8 1719.11   157.4 1716.14
   182.6 1714.81   186.2 1713.93     197 1709.33   200.6 1708.16   210.9 1706.33
     215 1706.45   223.3 1707.65   225.8 1707.62   230.51706.295   233.6 1705.24
   240.2 1704.66   243.8 1705.02   246.91706.566   248.1 1707.35     253 1711.94
   254.6 1713.05   255.5  1713.2     258 1713.14   265.4 1711.78   279.3 1710.97
   309.2 1711.66   325.8 1712.46   339.1 1713.71   386.5 1726.91   408.6 1734.41
#Mann= 3 ,-1 , 0
       0      .1       0   230.5    .045       0   246.9      .1       0
#XS Ineff= 2 , 0
                          255.93         1714.72
Permanent Ineff=
       F       F
Bank Sta=230.5,246.9
XS Rating Curve= 0 ,0
Exp/Cntr(USF)=0,0
Exp/Cntr=0.3,0.1

Type RM Length L Ch R = 1 ,248     ,258.5,248.4,238
XS GIS Cut Line= 4
 2023986.1830227249365.2356849122023994.34304366249249.738233795
2023825.17344764249198.0165056192023641.80751199249284.879840069
#Sta/Elev= 30
       0 1715.37    34.9 1713.19    80.9 1711.79    90.8 1711.08   151.6 1710.21
   158.4 1709.11   168.7 1704.72   180.2 1703.05   189.31700.993   192.7 1700.27
   199.6 1699.68   206.5 1700.25   209.2 1701.07   216.7 1702.95   233.9 1704.52
   247.6 1706.95   254.5  1707.6   292.7 1707.12   346.6  1707.9   362.2 1707.61
   397.5 1706.06   415.6 1706.45   421.4 1706.99   428.7 1708.37   433.8 1710.16
   441.1 1713.95   451.9 1721.14   460.8 1725.44   473.7 1730.57   495.6 1736.89
#Mann= 4 ,-1 , 0
       0    .035       0   189.3    .045       0   209.2    .035       0
  422.69      .1       0
#XS Ineff= 2 , 0
                          261.97         1711.06
Permanent Ineff=
       F       F
Bank Sta=189.3,209.2
XS Rating Curve= 0 ,0
Exp/Cntr(USF)=0,0
Exp/Cntr=0.3,0.1

Type RM Length L Ch R = 1 ,0       ,326.1,324.4,322.8
XS GIS Cut Line= 2
2024292.14400308248881.6032236262023521.14238447249091.273469268
#Sta/Elev= 30
       0 1721.24    24.1 1721.36    41.5 1719.33    68.7 1710.33    99.3 1704.13
   214.9 1703.41   303.3 1700.52   347.5 1699.56   350.9 1699.08   361.1 1694.02
   367.9 1692.56   388.3 1692.92     393 1694.08     401 1699.46   405.3 1700.88
   429.1 1701.91   500.5 1700.18   582.1  1702.4   595.7 1699.57   605.9 1699.06
   619.5 1698.99   660.3  1702.9   673.9  1706.3   697.7 1717.12   724.9 1733.89
   748.7 1751.48   765.7  1765.7   775.9 1772.48   783.2 1780.23     799 1790.71
#Mann= 6 ,-1 , 0
       0    .035       0   303.3     .04       0   361.1    .045       0
     393     .04       0     401    .035       0   605.9      .1       0
#XS Ineff= 2 , 0
             345    1704     430            1704
Permanent Ineff=
       F       F
Bank Sta=361.1,393
XS Rating Curve= 0 ,0
Exp/Cntr(USF)=0,0
Exp/Cntr=0.3,0.1
LCMann Table=0

Chan Stop Cuts=-1
Use User Specified Reach Order=0
Composite Channel Slope=5